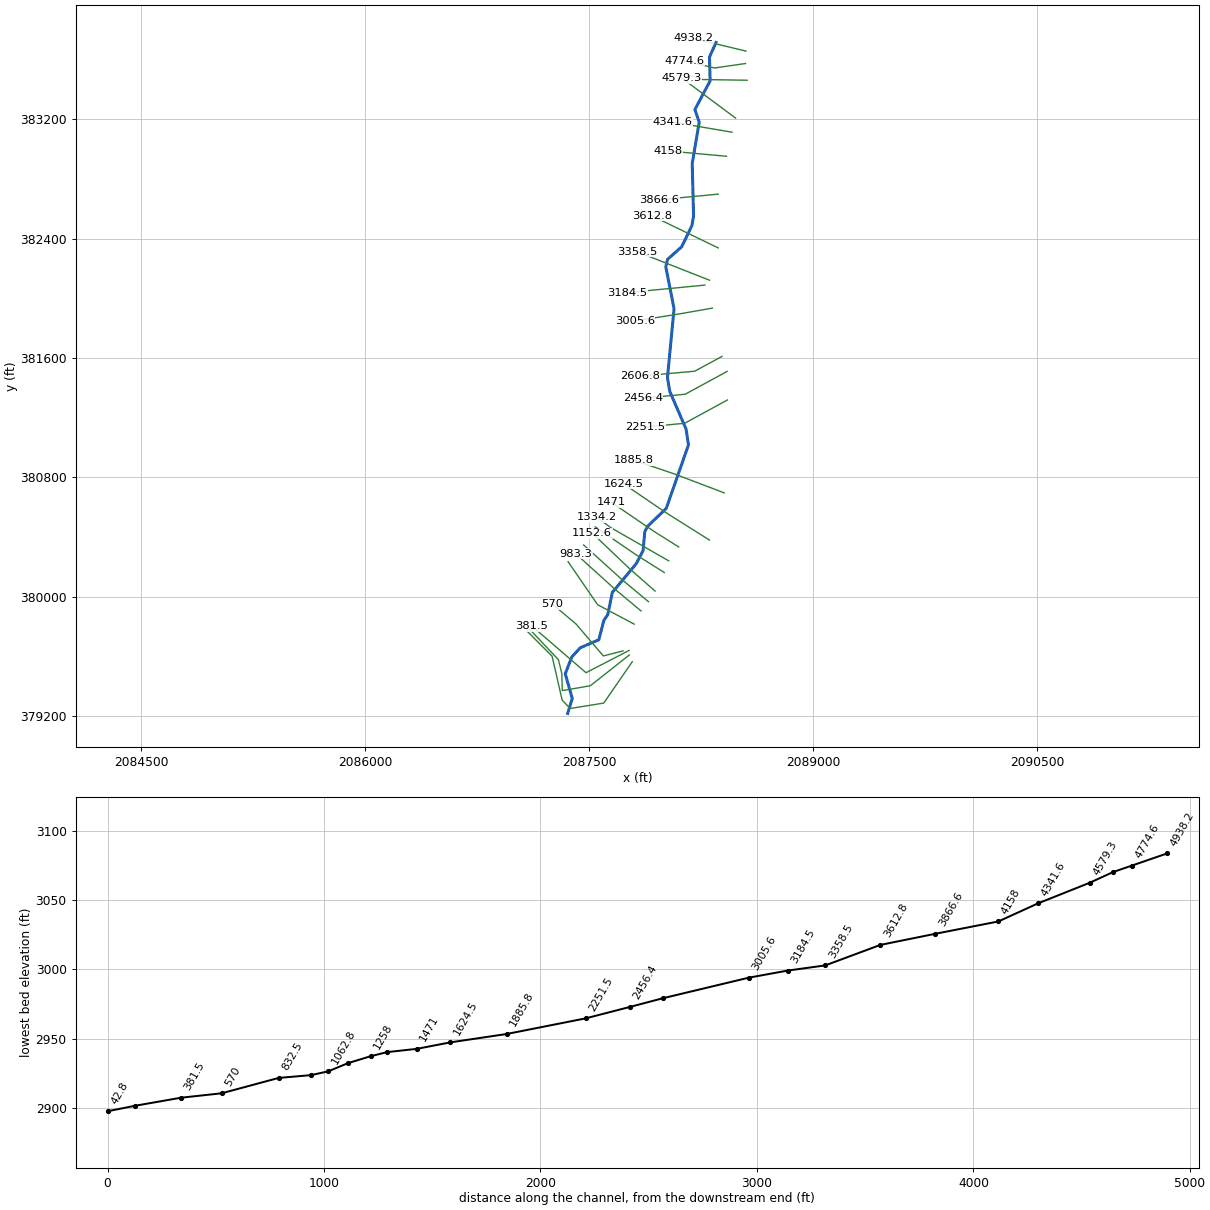
--- SmokehseBr.prj (project) ---

Proj Title=SmokehseBr
Current Plan=p01
Default Exp/Contr=0,0
English Units
Geom File=g01
Flow File=f01
Plan File=p01
BEGIN DESCRIPTION:
END DESCRIPTION:
DSS Export Rating Curves= 0
DSS Export Rating Curve Sorted= 0
DSS Export Volume Flow Curves= 0
DXF OffsetX= 0
DXF OffsetY= 0
DXF ScaleX= 0
DXF ScaleY= 0

--- SmokehseBr.p01 (plan) ---

Plan Title=Floodplain
Program Version=4.00
Geom File=g01
Flow File=f01
K Sum by GR=0
Std Step Tol=0.01
Critical Tol=0.01
Num of Std Step Trials=20
Max Error Tol=0.3
Flow Tol Ratio=0.001
Split Flow NTrial=30
Split Flow Tol=0.02
Split Flow Ratio=0.02
Log Output Level=0
Friction Slope Method=1
Unsteady Friction Slope Method=2
Unsteady Bridges Friction Slope Method=1
Global Log Level=0
CheckData=False
Run HTab=0
Run UNet=0
Run PostProcess=0
UNET Theta=0
UNET Theta Warmup=0
UNET ZTol=0
UNET ZSATol=0
UNET MxIter=0
UNET MaxInSteps=0
UNET DtIC=0
UNET DtMin=0
UNET MaxCRTS=0
UNET WFStab=0
UNET SFStab=0
UNET WFX=0
UNET SFX=0
UNET DSS MLevel=0
UNET DZMax Abort=0
UNET Convert EG Bridges=0
UNET Use Existing IB Tables=0
UNET Froude Limit=0
UNET Froude Power=0
Write IC File=0
Echo Input=False
Echo Output=False
Write Detailed=0

--- SmokehseBr.f01 (steady flow) ---

Flow Title=NFF Regression Equation
Program Version=4.00
Number of Profiles=1
Profile Names=P100yr
River Rch & RM=SmokehseBr,Main      ,4938.2
525.3643
River Rch & RM=SmokehseBr,Main      ,2456.4
564.1575
River Rch & RM=SmokehseBr,Main      ,1885.8
649.6235
River Rch & RM=SmokehseBr,Main      ,381.5
672.9647
Boundary for River Rch & Prof#=SmokehseBr,Main      ,1
Up Type=0
Dn Type=3
Dn Slope=0.025239

--- SmokehseBr.g01 (geometry) ---

Geom Title=USGS 10m DEM
Program Version=4.00

River Reach=SmokehseBr      ,Main
Reach XY= 30
     2088348.915      383714.581     2088304.673       383616.94
     2088309.106      383457.364     2088207.154      383265.281
     2088235.949      383179.528     2088189.121      382903.163
     2088198.289      382550.143     2088186.468       382485.13
     2088118.501      382344.762     2088023.937      382260.542
     2088012.116      382211.782     2088067.542      381929.276
     2088023.335      381467.243      2088039.25      381374.206
     2088148.052      381122.822     2088164.009      381016.568
     2088015.217      380590.834     2087890.322      380470.935
     2087871.588      380434.715      2087860.12       380307.69
     2087814.395      380220.267     2087653.935      380026.951
     2087623.637      379878.369      2087597.35      379839.683
     2087563.929      379709.973     2087438.818       379656.17
     2087382.895      379594.462     2087339.029      379482.197
     2087386.099      379316.399     2087355.187      379216.639

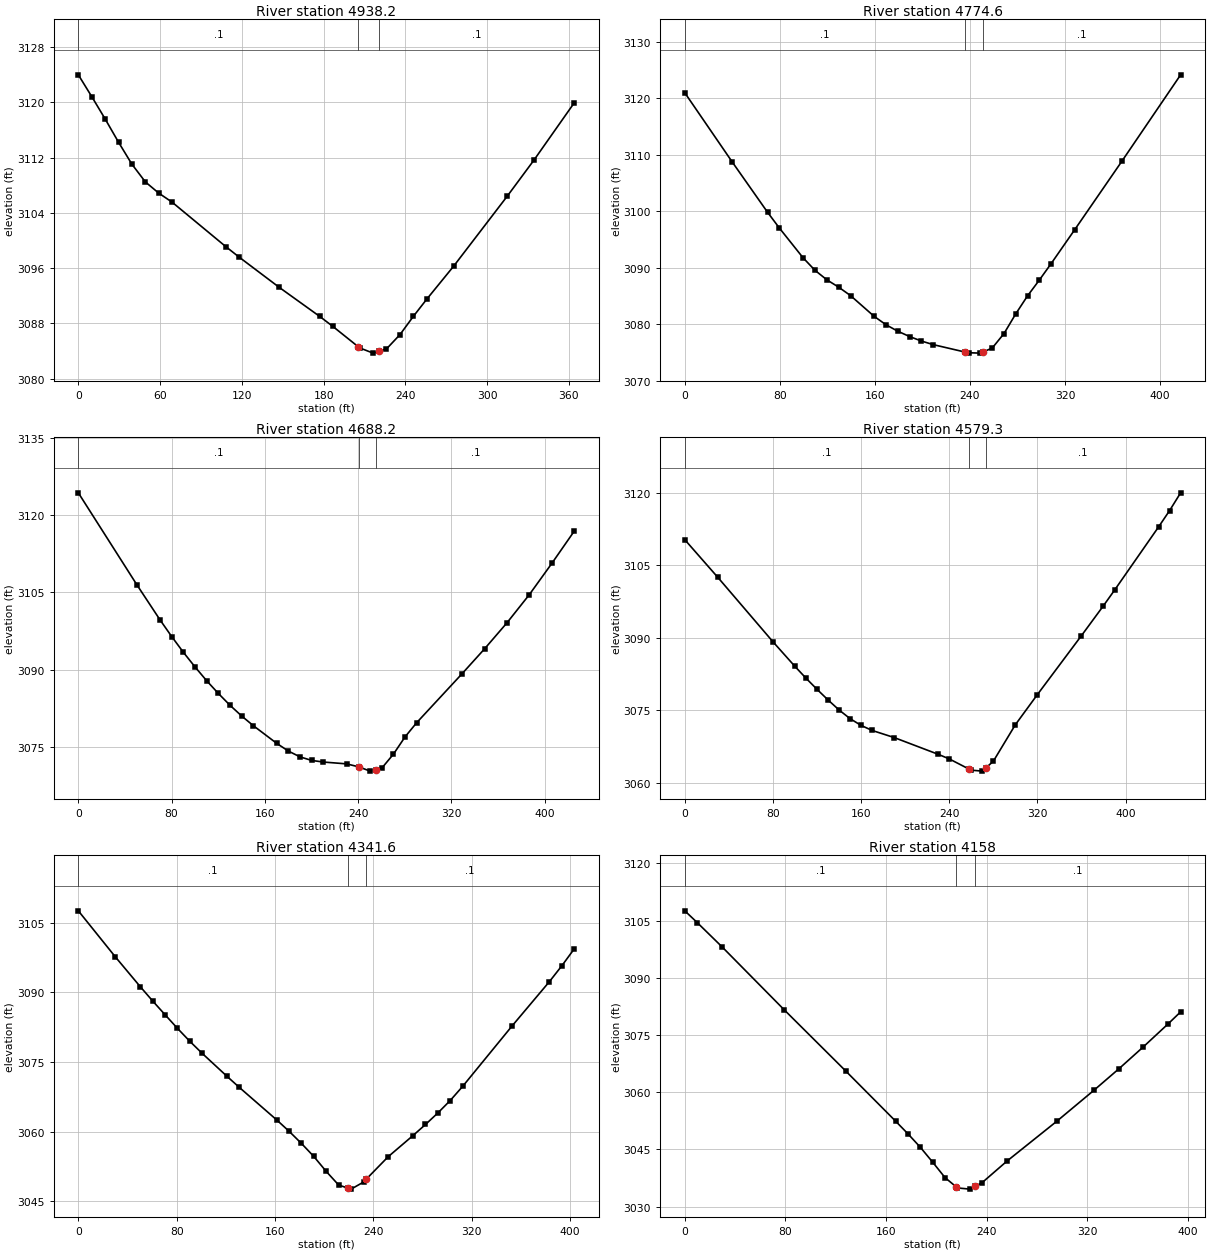
Type RM Length L Ch R = 1 ,4938.2  ,164.6,163.6,162.8
XS GIS Cut Line= 2
     2088549.041      383656.746      2088195.52      383742.414
#Sta/Elev= 25
       0 3123.98     9.8 3120.84    19.7 3117.58    29.5 3114.22    39.3 3111.04
    49.2 3108.47      59 3106.85    68.8 3105.54   108.1 3099.12     118 3097.58
   147.5 3093.19     177 3089.01   186.8 3087.54   205.4  3084.6   206.4 3084.44
   216.3 3083.68   220.4 3083.94   226.1 3084.29     236 3086.36   245.8    3089
   255.6 3091.48   275.3 3096.25   314.6 3106.38   334.3 3111.63   363.8 3119.91
#Mann= 3 , 0 , 0
       0      .1       0   205.4    .045       0   220.4      .1       0
Bank Sta=205.4,220.4
XS Rating Curve= 0 ,0
Exp/Cntr=0.3,0.1

Type RM Length L Ch R = 1 ,4774.6  ,81.2,86.3,91.4
XS GIS Cut Line= 3
     2088545.873      383573.672     2088338.828      383543.643
     2088136.525      383592.638
#Sta/Elev= 28
       0 3120.96    39.8 3108.75    69.7  3099.8    79.7 3096.99    99.6 3091.74
   109.6 3089.53   119.6 3087.85   129.5 3086.55   139.5 3085.06   159.4 3081.38
   169.4 3079.89   179.3 3078.75   189.3  3077.8   199.2 3077.01   209.2 3076.37
   235.7 3075.07     239 3074.94   248.9 3074.87   250.7 3075.04   258.8 3075.77
   268.7 3078.33   278.6 3081.82   288.5    3085   298.4 3087.79   308.3 3090.69
   328.2 3096.71   367.8  3108.8   417.4 3124.14
#Mann= 3 , 0 , 0
       0      .1       0   235.7    .045       0   250.7      .1       0
Bank Sta=235.7,250.7
XS Rating Curve= 0 ,0
Exp/Cntr=0.3,0.1

Type RM Length L Ch R = 1 ,4688.2  ,123.2,109,94.8
XS GIS Cut Line= 3
     2088556.937      383461.457     2088256.643      383466.198
     2088138.106      383505.711
#Sta/Elev= 30
       0  3124.4    50.1 3106.54    70.1 3099.66    80.1 3096.42    90.1 3093.36
   100.1 3090.51   110.1 3087.82   120.1 3085.35   130.1 3083.05   140.2 3080.94
   150.2 3079.06   170.2 3075.63   180.2 3074.13   190.2    3073   200.2 3072.31
   210.2    3072   230.2 3071.64   240.7 3071.05   250.3 3070.23   255.7 3070.54
   260.3 3070.81   270.3 3073.54   280.3 3076.91   290.3 3079.68   329.2  3089.2
   348.4 3094.02   367.6 3099.08   386.8 3104.57   406.1 3110.65   425.3 3116.92
#Mann= 3 , 0 , 0
       0      .1       0   240.7    .045       0   255.7      .1       0
Bank Sta=240.7,255.7
XS Rating Curve= 0 ,0
Exp/Cntr=0.3,0.1

Type RM Length L Ch R = 1 ,4579.3  ,226.6,237.7,248.8
XS GIS Cut Line= 2
       2088479.7      383207.555     2088118.974      383476.517
#Sta/Elev= 27
       0 3110.33      30 3102.53      80 3089.21     100  3084.1     110 3081.67
     120 3079.37     130 3077.17     140  3075.1     150  3073.3     160  3071.9
     170 3070.86     190 3069.39     230 3065.92     240 3064.97     258 3062.86
     260 3062.64     270 3062.44     273 3063.06     280 3064.48     300 3072.04
     320 3078.28     360 3090.48     380 3096.68     390 3099.88     430 3112.98
     440 3116.36     450 3120.03
#Mann= 3 , 0 , 0
       0      .1       0     258    .045       0     273      .1       0
Bank Sta=258,273
XS Rating Curve= 0 ,0
Exp/Cntr=0.3,0.1

Type RM Length L Ch R = 1 ,4341.6  ,181.8,183.6,185.4
XS GIS Cut Line= 2
     2088455.732      383113.094     2088058.283      383181.133
#Sta/Elev= 30
       0 3107.59    30.2 3097.64    50.4 3091.24    60.5 3088.16    70.6 3085.19
    80.6 3082.28    90.7 3079.48   100.8 3076.87     121 3071.92     131 3069.54
   161.3 3062.56   171.4 3060.11   181.4  3057.5   191.5 3054.68   201.6 3051.46
   211.7 3048.53     219 3047.89   221.8 3047.65   231.9 3049.17     234 3049.76
     252 3054.64   272.2  3059.2   282.3 3061.57   292.3 3064.04   302.4 3066.73
   312.5 3069.77   352.8 3082.82   383.1 3092.35   393.2 3095.76   403.2 3099.38
#Mann= 3 , 0 , 0
       0      .1       0     219    .045       0     234      .1       0
Bank Sta=219,234
XS Rating Curve= 0 ,0
Exp/Cntr=0.3,0.1

Type RM Length L Ch R = 1 ,4158    ,287.2,291.4,295.6
XS GIS Cut Line= 2
     2088418.753      382951.674     2088026.048      382987.723
#Sta/Elev= 22
       0 3107.58     9.9 3104.49    29.6 3098.14    78.9 3081.67   128.2  3065.5
   167.6 3052.43   177.5 3049.08   187.3 3045.57   197.2 3041.63     207 3037.59
     216 3035.13   216.9 3034.88   226.8 3034.57     231 3035.32   236.6  3036.3
   256.3 3041.93   295.8 3052.35   325.3 3060.46   345.1 3066.08   364.8 3071.91
   384.5 3077.94   394.4 3081.07
#Mann= 3 , 0 , 0
       0      .1       0     216    .045       0     231      .1       0
Bank Sta=216,231
XS Rating Curve= 0 ,0
Exp/Cntr=0.3,0.1

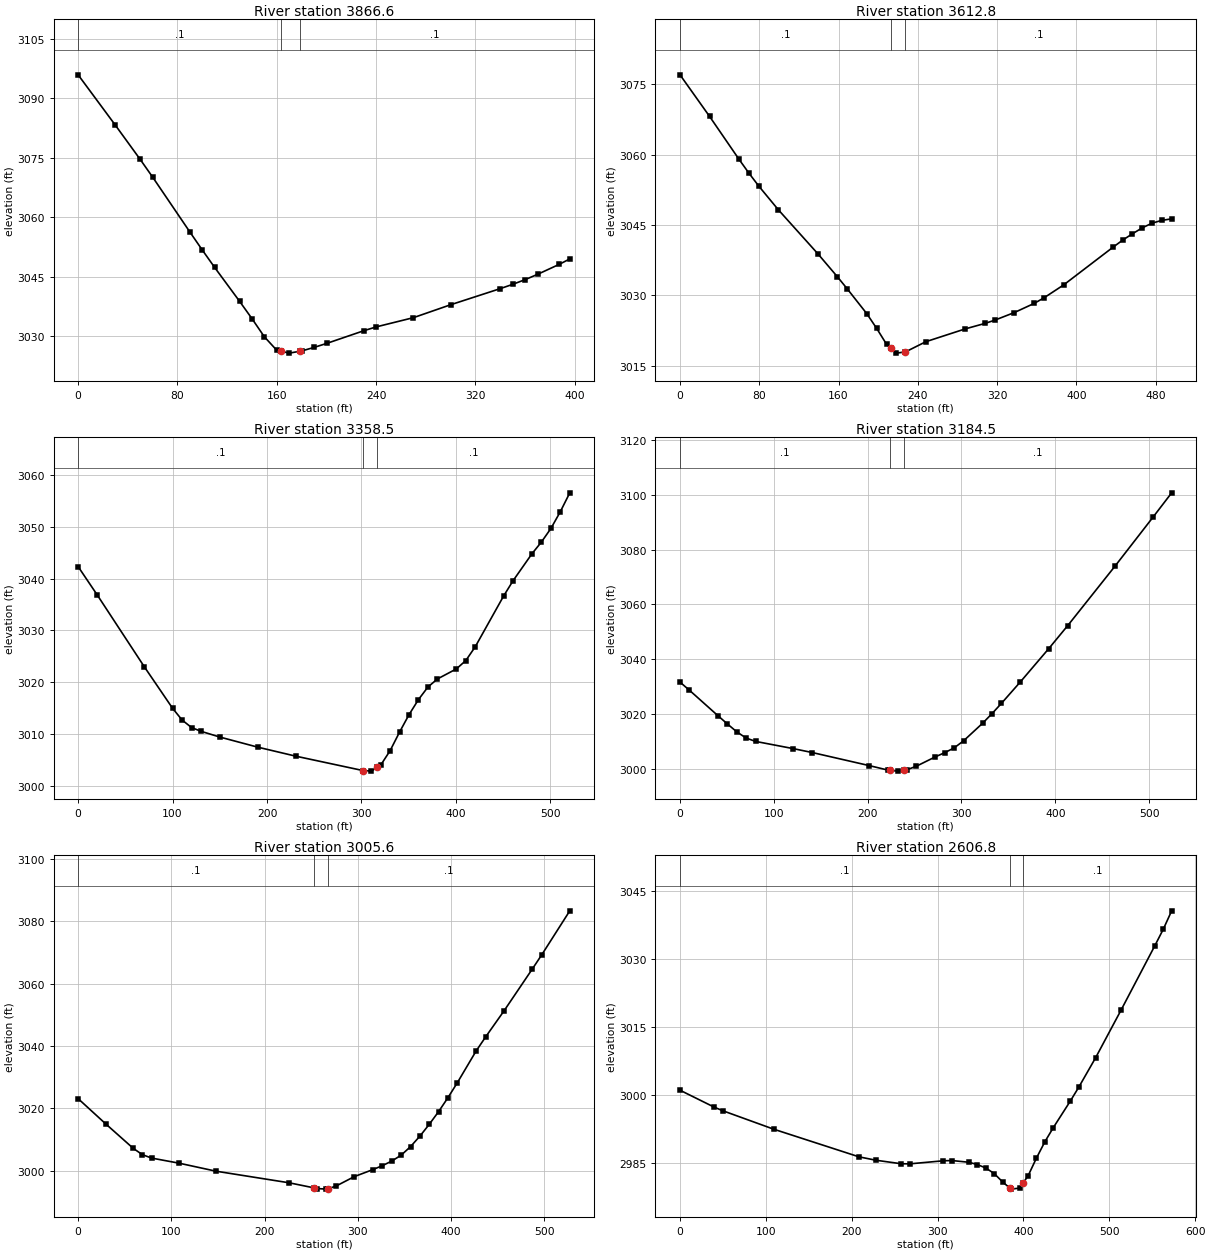
Type RM Length L Ch R = 1 ,3866.6  ,266.1,253.7,241.4
XS GIS Cut Line= 3
     2088363.152      382697.993     2087994.729      382662.578
      2087969.01      382660.105
#Sta/Elev= 27
       0 3095.88      30 3083.17      50 3074.54      60 3070.09      90 3056.24
     100 3051.69     110 3047.28     130 3038.77     140 3034.39     150  3029.8
     160  3026.4   163.4 3026.16   170.1 3025.68   178.4 3026.14   180.1 3026.23
   190.1 3027.13   200.1 3028.12   230.1 3031.33   240.1  3032.3   270.1 3034.63
   300.1 3037.89   340.1 3041.96   350.1 3043.04   360.1 3044.23   370.1 3045.56
   387.4 3048.06     396 3049.44
#Mann= 3 , 0 , 0
       0      .1       0   163.4    .045       0   178.4      .1       0
Bank Sta=163.4,178.4
XS Rating Curve= 0 ,0
Exp/Cntr=0.3,0.1

Type RM Length L Ch R = 1 ,3612.8  ,252.4,254.3,256.2
XS GIS Cut Line= 2
     2088363.444      382337.207     2087917.002      382553.612
#Sta/Elev= 30
       0 3077.01    29.8 3068.15    59.5    3059    69.5 3056.05    79.4  3053.3
    99.2 3048.23   138.9 3038.89   158.8 3033.94   168.7 3031.37   188.5 3026.06
   198.4 3022.94   208.4 3019.54   212.5 3018.75   218.3 3017.65   227.5 3017.91
   248.1 3020.09   287.8 3022.82   307.6 3023.98   317.5 3024.67   337.4 3026.31
   357.2 3028.24   367.1 3029.42     387 3032.18   436.6 3040.19   446.5 3041.73
   456.4 3043.09   466.4 3044.37   476.3 3045.37   486.2 3045.97   496.1 3046.29
#Mann= 3 , 0 , 0
       0      .1       0   212.5    .045       0   227.5      .1       0
Bank Sta=212.5,227.5
XS Rating Curve= 0 ,0
Exp/Cntr=0.3,0.1

Type RM Length L Ch R = 1 ,3358.5  ,163.3,174,184.7
XS GIS Cut Line= 2
     2088305.023      382120.707     2087820.758      382311.822
#Sta/Elev= 30
       0  3042.3      20  3036.9    70.1 3022.99   100.1 3014.97   110.1 3012.73
   120.1 3011.28   130.2 3010.55   150.2 3009.44   190.2  3007.5   230.3 3005.77
   301.6 3002.99   310.4 3002.88   316.6  3003.6   320.4 3004.04   330.4 3006.84
   340.4 3010.42   350.4 3013.77   360.4 3016.68   370.4 3019.09   380.4 3020.64
   400.5 3022.58   410.5 3024.19   420.5 3026.85   450.5 3036.62   460.5 3039.57
   480.6 3044.79   490.6 3047.05   500.6 3049.65   510.6 3052.89   520.6 3056.52
#Mann= 3 , 0 , 0
       0      .1       0   301.6    .045       0   316.6      .1       0
Bank Sta=301.6,316.6
XS Rating Curve= 0 ,0
Exp/Cntr=0.3,0.1

Type RM Length L Ch R = 1 ,3184.5  ,177.4,178.9,180.3
XS GIS Cut Line= 2
     2088274.028      382088.007     2087752.465      382037.431
#Sta/Elev= 29
       0  3031.6    10.1 3028.63    40.3 3019.39    50.4 3016.38    60.5 3013.47
    70.5 3011.19    80.6 3009.97   120.9 3007.33   141.1  3005.9   201.5 3001.16
   221.7  2999.5   224.2 2999.41   231.8 2999.13   239.2 2999.49   241.8 2999.62
   251.9 3000.92   272.1 3004.34   282.2 3005.88   292.2 3007.61   302.3 3010.21
   322.5  3016.6   332.5  3020.1   342.6 3023.87   362.8 3031.71     393 3043.83
   413.2 3052.22   463.6 3073.92   503.9  3091.7     524 3100.68
#Mann= 3 , 0 , 0
       0      .1       0   224.2    .045       0   239.2      .1       0
Bank Sta=224.2,239.2
XS Rating Curve= 0 ,0
Exp/Cntr=0.3,0.1

Type RM Length L Ch R = 1 ,3005.6  ,400.5,398.8,397.2
XS GIS Cut Line= 3
     2088324.126      381933.636     2088081.681      381891.098
     2087803.604      381847.492
#Sta/Elev= 30
       0 3023.07    29.5    3015    59.1 3007.13    68.9  3005.1    78.8    3004
   108.3 3002.36   147.7  2999.8   226.5 2996.06     253 2994.44   256.2 2994.23
   266.2 2994.03     268 2994.19   276.3 2994.94   296.4 2998.05   316.5 3000.32
   326.6 3001.58   336.6 3003.04   346.7 3004.94   356.7 3007.67   366.8 3011.05
   376.8 3014.83   386.9 3018.94   396.9  3023.4     407 3028.22   427.1 3038.37
   437.2 3042.84   457.3 3051.36   487.4 3064.68   497.5 3069.23   527.6 3083.35
#Mann= 3 , 0 , 0
       0      .1       0     253    .045       0     268      .1       0
Bank Sta=253,268
XS Rating Curve= 0 ,0
Exp/Cntr=0.3,0.1

Type RM Length L Ch R = 1 ,2606.8  ,150.5,150.4,150.3
XS GIS Cut Line= 3
     2088388.827      381609.969     2088205.548      381510.555
      2087842.76      381478.276
#Sta/Elev= 30
       0    3001    39.7 2997.27    49.6 2996.48   109.2 2992.38   208.5 2986.27
   228.2 2985.52   257.7 2984.74   267.6 2984.72   306.9  2985.4   316.8 2985.45
   336.5 2985.07   346.3 2984.57   356.2  2983.8     366 2982.57   375.8 2980.72
   384.7 2979.29   385.7 2979.13   395.5 2979.36   399.7  2980.5   405.4 2982.05
   415.2    2986   425.1 2989.64   434.9 2992.75   454.6 2998.59   464.4 3001.64
   484.1 3008.18   513.7  3018.7     553 3032.92   562.9 3036.59   572.7 3040.67
#Mann= 3 , 0 , 0
       0      .1       0   384.7    .045       0   399.7      .1       0
Bank Sta=384.7,399.7
XS Rating Curve= 0 ,0
Exp/Cntr=0.3,0.1

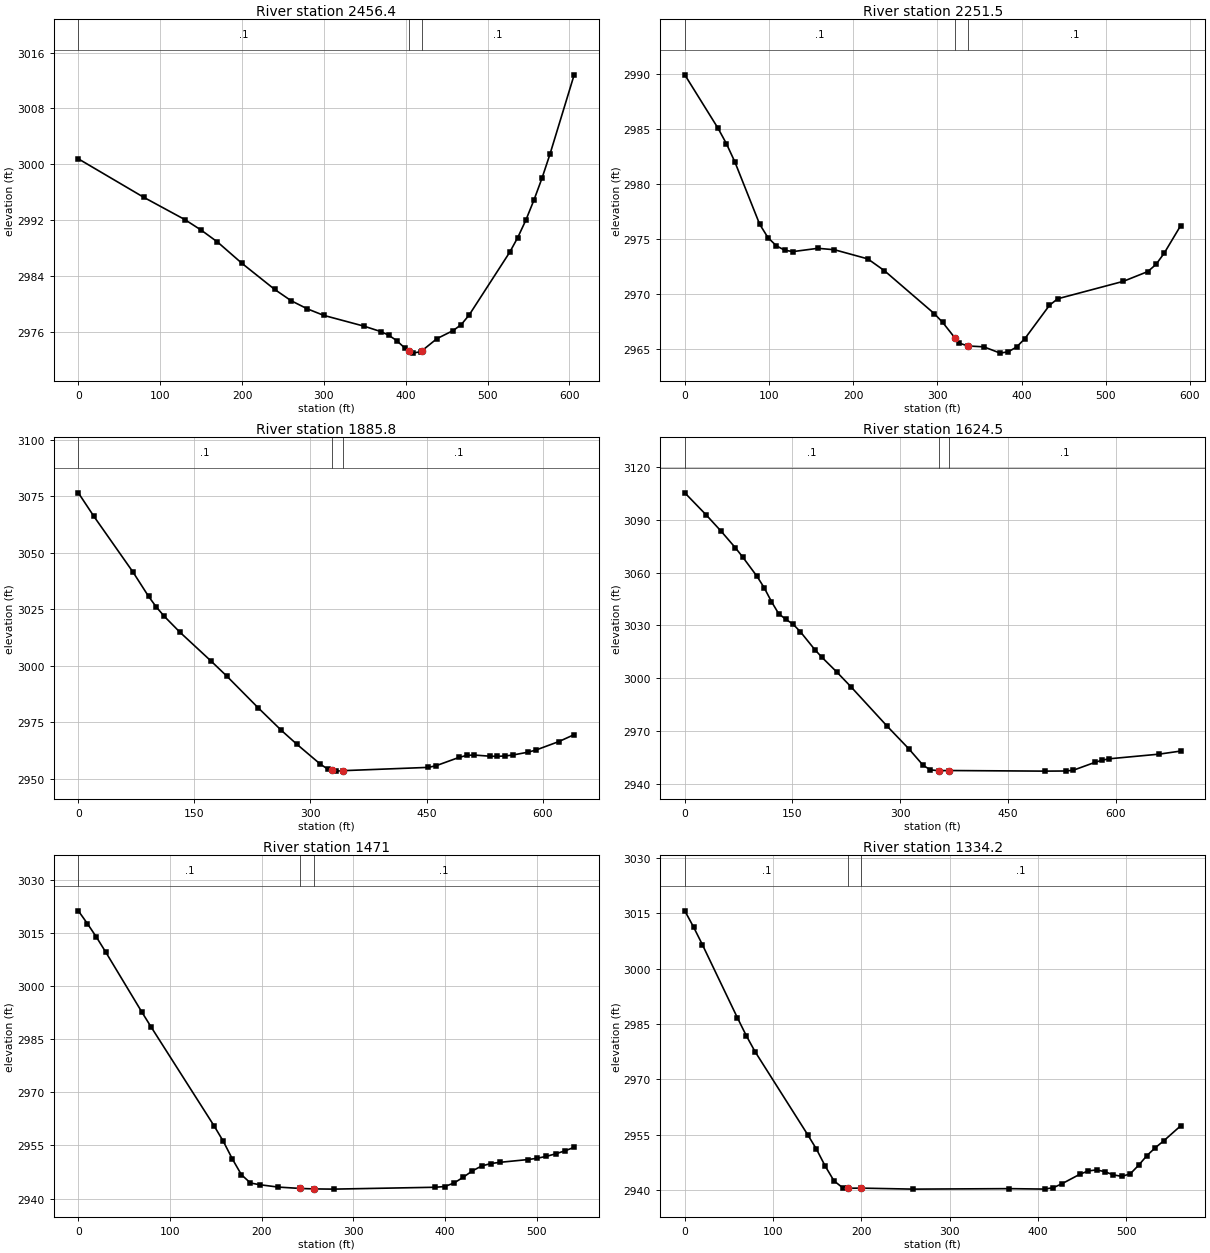
Type RM Length L Ch R = 1 ,2456.4  ,196.6,204.9,205.1
XS GIS Cut Line= 3
      2088423.21      381509.463     2088142.296      381356.416
     2087857.671      381329.167
#Sta/Elev= 30
       0 3000.78      80 2995.26     130 2992.08     150 2990.57     170 2988.86
   199.9  2985.8   239.9 2982.06   259.9 2980.45   279.9 2979.27   299.9 2978.34
   349.5 2976.78   369.2 2976.03   379.1 2975.51   388.9 2974.73   398.8 2973.67
   404.3 2973.26   408.6 2972.93   418.5 2973.14   419.3 2973.22   438.2 2975.01
   457.9 2976.16   467.8 2977.01   477.6 2978.41     527 2987.38   536.8 2989.48
   546.7 2991.97   556.5 2994.82   566.4 2997.97   576.2 3001.43   605.8 3012.82
#Mann= 3 , 0 , 0
       0      .1       0   404.3    .045       0   419.3      .1       0
Bank Sta=404.3,419.3
XS Rating Curve= 0 ,0
Exp/Cntr=0.3,0.1

Type RM Length L Ch R = 1 ,2251.5  ,384.2,365.7,355.5
XS GIS Cut Line= 3
     2088424.997      381317.689      2088138.71      381161.715
     2087876.922      381136.652
#Sta/Elev= 30
       0 2989.91    39.5 2985.06    49.4 2983.67    59.3 2982.04    88.9 2976.36
    98.8 2975.14   108.7  2974.4   118.6    2974   128.4 2973.87   158.1 2974.17
   177.8 2974.04   217.4 2973.21   237.1 2972.14   296.4 2968.24   306.3 2967.45
   321.3    2966     326 2965.57   336.3 2965.31   355.2 2965.23   374.7 2964.66
   384.5 2964.79   394.2 2965.22   403.9 2965.97   433.2    2969   442.9 2969.59
   520.8 2971.17     550 2972.06   559.8 2972.71   569.5 2973.73     589 2976.22
#Mann= 3 , 0 , 0
       0      .1       0   321.3    .045       0   336.3      .1       0
Bank Sta=321.3,336.3
XS Rating Curve= 0 ,0
Exp/Cntr=0.3,0.1

Type RM Length L Ch R = 1 ,1885.8  ,266.1,261.3,255.8
XS GIS Cut Line= 3
     2088403.268      380695.118     2088073.134      380820.779
     2087801.051      380913.586
#Sta/Elev= 30
       0 3076.52    20.2 3066.06    70.6 3041.47    90.8 3030.67   100.9 3025.92
     111  3021.9   131.2 3014.86   171.6 3002.04   191.8 2995.42   232.1 2981.48
   262.4 2971.38   282.6 2965.19   312.9  2956.4     323 2954.11   327.6 2953.77
   333.1 2953.36   342.6 2953.57   452.4 2955.02   462.3 2955.76     492 2959.44
   501.9 2960.33   511.8 2960.47   531.7 2959.97   541.6 2959.91   551.5 2960.07
   561.4 2960.49   581.2 2961.75   591.2 2962.68   620.9 2966.44   640.7 2969.51
#Mann= 3 , 0 , 0
       0      .1       0   327.6    .045       0   342.6      .1       0
Bank Sta=327.6,342.6
XS Rating Curve= 0 ,0
Exp/Cntr=0.3,0.1

Type RM Length L Ch R = 1 ,1624.5  ,153.9,153.5,153.6
XS GIS Cut Line= 3
     2088304.922      380378.456     2088007.027      380566.241
       2087727.6      380757.189
#Sta/Elev= 30
       0 3105.21    30.2  3092.5    50.3 3083.55    70.4 3074.06    80.5 3068.86
   100.6 3057.82   110.7 3051.27   120.7 3043.49   130.8  3036.6   140.9 3033.39
   150.9 3030.64     161 3026.36   181.1 3016.24   191.2  3011.8   211.3 3003.71
   231.4 2995.17   281.7 2972.86   311.9 2960.02     332 2950.58   342.1    2948
   353.4 2947.57   368.4 2947.64   501.4  2947.3   531.3 2947.38   541.3 2947.84
   571.1 2952.25   581.1 2953.49     591 2954.29   660.7 2956.94   690.6 2958.68
#Mann= 3 , 0 , 0
       0      .1       0   353.4    .045       0   368.4      .1       0
Bank Sta=353.4,368.4
XS Rating Curve= 0 ,0
Exp/Cntr=0.3,0.1

Type RM Length L Ch R = 1 ,1471    ,135.2,136.8,138.3
XS GIS Cut Line= 3
     2088098.725      380332.448     2087931.478      380437.876
     2087648.043      380631.562
#Sta/Elev= 30
       0 3021.18     9.9 3017.57    19.8 3013.74    29.7 3009.62    69.2 2992.66
    79.1 2988.53   148.3 2960.43   158.2 2956.13     168 2951.19   177.9 2946.73
   187.8 2944.38   197.7  2943.9   217.9 2943.23   242.3 2942.84   257.3 2942.71
   278.5 2942.65   389.5 2943.18   399.6 2943.38   409.7 2944.34   419.8 2945.97
   429.9 2947.79     440 2949.17   450.1 2949.87   460.2 2950.22   490.5 2950.99
   500.6 2951.36   510.7  2951.9   520.8 2952.61   530.9 2953.45     541 2954.45
#Mann= 3 , 0 , 0
       0      .1       0   242.3    .045       0   257.3      .1       0
Bank Sta=242.3,257.3
XS Rating Curve= 0 ,0
Exp/Cntr=0.3,0.1

Type RM Length L Ch R = 1 ,1334.2  ,76.9,76.2,75.6
XS GIS Cut Line= 3
     2088031.946      380239.153     2087644.245      380461.911
     2087552.421      380529.929
#Sta/Elev= 30
       0 3015.61     9.9 3011.24    19.9 3006.46    59.6 2986.66    69.6 2981.84
    79.5 2977.53   139.1 2955.05     149 2951.16     159 2946.53   168.9 2942.56
   178.9 2940.65   184.6 2940.55   199.6 2940.58   258.4 2940.31   367.6 2940.44
   407.4 2940.32   417.3  2940.7   427.3  2941.8   447.1 2944.31   456.7 2945.22
   466.2 2945.52   475.7 2945.02   485.2 2944.16   494.8 2943.77   504.3 2944.43
   513.8 2946.76   523.3  2949.4   532.8 2951.53   542.4  2953.4   561.4 2957.43
#Mann= 3 , 0 , 0
       0      .1       0   184.6    .045       0   199.6      .1       0
Bank Sta=184.6,199.6
XS Rating Curve= 0 ,0
Exp/Cntr=0.3,0.1

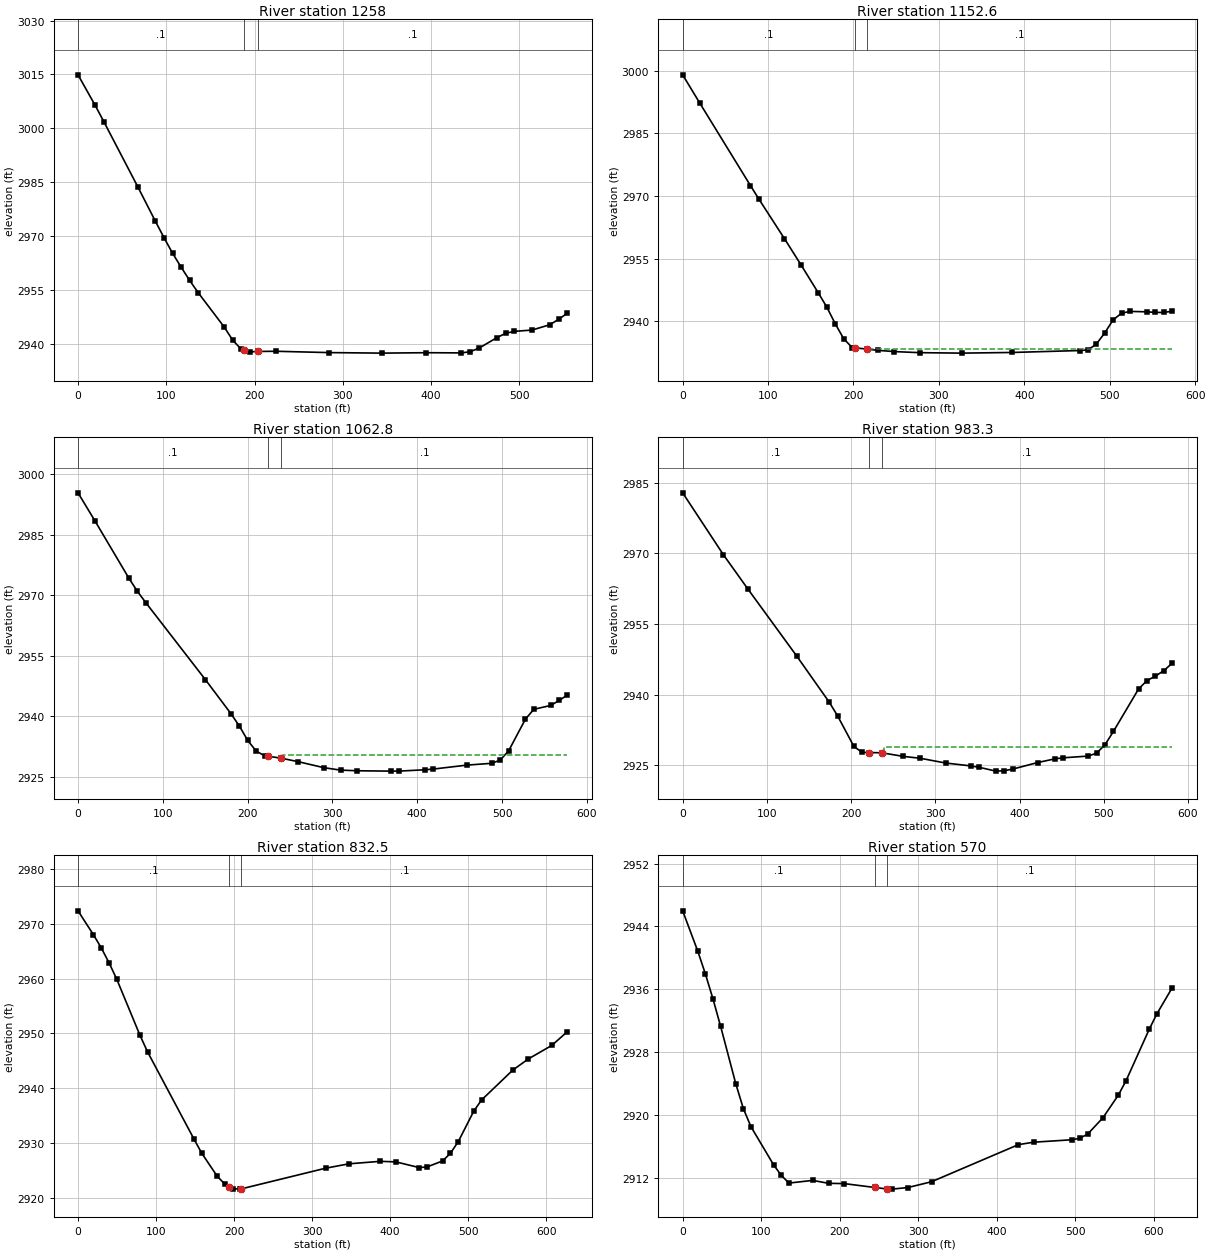
Type RM Length L Ch R = 1 ,1258    ,109,105.5,101.8
XS GIS Cut Line= 3
     2088002.273      380160.865     2087812.892      380280.246
     2087539.928      380466.777
#Sta/Elev= 30
       0  3014.9    19.5 3006.36    29.2 3001.88    68.1 2983.52    87.6 2974.12
    97.3 2969.57   107.1  2965.2   116.8  2961.3   126.5  2957.6   136.3 2954.14
   165.5 2944.66   175.2 2940.98   184.9 2938.43   188.5 2938.16   194.7  2937.7
   203.5 2937.81   223.9 2937.87     284  2937.5   344.1 2937.35   394.2 2937.47
   434.3 2937.41   444.3 2937.75   454.3 2938.74   474.3 2941.63   484.4 2942.88
   494.4 2943.42   514.4 2943.78   534.4 2945.26   544.5 2946.77   554.5 2948.51
#Mann= 3 , 0 , 0
       0      .1       0   188.5    .045       0   203.5      .1       0
Bank Sta=188.5,203.5
XS Rating Curve= 0 ,0
Exp/Cntr=0.3,0.1

Type RM Length L Ch R = 1 ,1152.6  ,89.3,89.8,89.4
XS GIS Cut Line= 3
     2087940.499      380036.597     2087769.061      380187.273
     2087519.522      380425.295
#Sta/Elev= 29
       0 2999.07    19.8 2992.37    79.4 2972.49    89.3 2969.24   119.1 2959.79
   138.9 2953.37   158.8 2946.76   168.7 2943.37   178.6 2939.37   188.6 2935.72
   198.5 2933.65   201.4 2933.58   216.4 2933.25   228.2 2932.97     248 2932.67
   277.5 2932.41   326.8  2932.3   385.9 2932.46   464.7 2932.92   474.6 2933.07
   484.4 2934.48   494.3 2937.18   504.1  2940.3     514 2941.89   523.8 2942.31
   543.5 2942.21   553.4 2942.07   563.2 2942.06   573.1 2942.35
#Mann= 3 , 0 , 0
       0      .1       0   201.4    .045       0   216.4      .1       0
#XS Ineff= 2 , 0
                          217.03         2933.38
Permanent Ineff=
       F       F
Bank Sta=201.4,216.4
XS Rating Curve= 0 ,0
Exp/Cntr=0.3,0.1

Type RM Length L Ch R = 1 ,1062.8  ,79.5,79.5,79.7
XS GIS Cut Line= 3
     2087896.334      379965.299     2087719.503       380112.81
     2087462.399      380345.686
#Sta/Elev= 30
       0 2995.33      20 2988.38    60.1 2974.16    70.1 2970.93    80.1 2968.11
   150.2  2949.1   180.2 2940.72   190.2 2937.64   200.2 2934.04   210.2  2931.4
   220.3 2930.24   224.5 2930.13   239.5 2929.67     260 2928.78   289.8 2927.32
   309.6 2926.71   329.4 2926.55     369 2926.46     379 2926.47   408.7 2926.79
   418.6 2926.96   458.2 2927.94     488  2928.4   497.9 2929.19   507.8 2931.48
   527.6 2939.32   537.5 2941.76   557.4 2942.71   567.3 2943.94   577.2  2945.3
#Mann= 3 , 0 , 0
       0      .1       0   224.5    .045       0   239.5      .1       0
#XS Ineff= 2 , 0
                          241.31         2930.47
Permanent Ineff=
       F       F
Bank Sta=224.5,239.5
XS Rating Curve= 0 ,0
Exp/Cntr=0.3,0.1

Type RM Length L Ch R = 1 ,983.3   ,147.1,150.8,155.3
XS GIS Cut Line= 3
     2087846.906      379903.236     2087668.511      380052.051
     2087409.896      380286.296
#Sta/Elev= 30
       0 2982.89    48.4 2969.72    77.4 2962.45   135.5 2948.17   174.2 2938.34
   183.9 2935.49   203.3 2928.98     213 2927.71   221.6 2927.68   236.6 2927.61
   262.2 2926.85   282.2 2926.45   312.1 2925.45     342 2924.83     352 2924.54
   371.9 2923.72   381.9 2923.81   391.8 2924.15   421.7 2925.55   441.7 2926.32
   451.6 2926.55   481.6 2926.92   491.5 2927.54   501.5 2929.33   511.5 2932.16
   541.4  2941.2   551.3 2942.96   561.3 2943.92   571.3 2945.07   581.2 2946.66
#Mann= 3 , 0 , 0
       0      .1       0   221.6    .045       0   236.6      .1       0
#XS Ineff= 2 , 0
                          239.13          2928.8
Permanent Ineff=
       F       F
Bank Sta=221.6,236.6
XS Rating Curve= 0 ,0
Exp/Cntr=0.3,0.1

Type RM Length L Ch R = 1 ,832.5   ,270.7,262.5,254.2
XS GIS Cut Line= 3
     2087800.741      379814.961     2087555.856      379945.057
     2087357.981      380233.671
#Sta/Elev= 30
       0 2972.32    19.8 2967.96    29.7  2965.6    39.6  2962.9    49.5 2959.92
    79.2 2949.73    89.1 2946.65   148.6 2930.77   158.5 2928.21   178.3 2924.02
   188.2 2922.56     194 2922.06   198.1 2921.72     208 2921.66     209  2921.7
   317.3 2925.47   347.3 2926.27   387.3 2926.72   407.3 2926.62   437.3 2925.58
   447.3  2925.7   467.3  2926.8   477.3  2928.2   487.3 2930.32   507.2 2935.88
   517.2  2937.9   557.2 2943.34   577.2 2945.37   607.2 2947.83   627.2 2950.34
#Mann= 3 , 0 , 0
       0      .1       0     194    .045       0     209      .1       0
Bank Sta=194,209
XS Rating Curve= 0 ,0
Exp/Cntr=0.3,0.1

Type RM Length L Ch R = 1 ,570     ,185.3,188.5,191.6
XS GIS Cut Line= 4
     2087725.461      379635.388     2087594.322      379601.667
     2087410.726      379816.486     2087253.359      379948.874
#Sta/Elev= 30
       0 2945.99    19.3 2940.85      29 2937.95    38.7 2934.76    48.4 2931.29
    67.7 2923.99    77.4 2920.82      87 2918.54   116.1 2913.65   125.7 2912.35
   135.4 2911.37   165.7 2911.71   185.9 2911.34     206  2911.3   244.7 2910.81
   259.7 2910.63   266.6  2910.6   286.8  2910.8   317.1 2911.54   427.8 2916.26
   447.4 2916.57   496.3 2916.88   506.1 2917.08   515.9 2917.59   535.5 2919.68
   555.1 2922.56   564.9 2924.39   594.3  2930.9     604 2932.86   623.6 2936.19
#Mann= 3 , 0 , 0
       0      .1       0   244.7    .045       0   259.7      .1       0
Bank Sta=244.7,259.7
XS Rating Curve= 0 ,0
Exp/Cntr=0.3,0.1

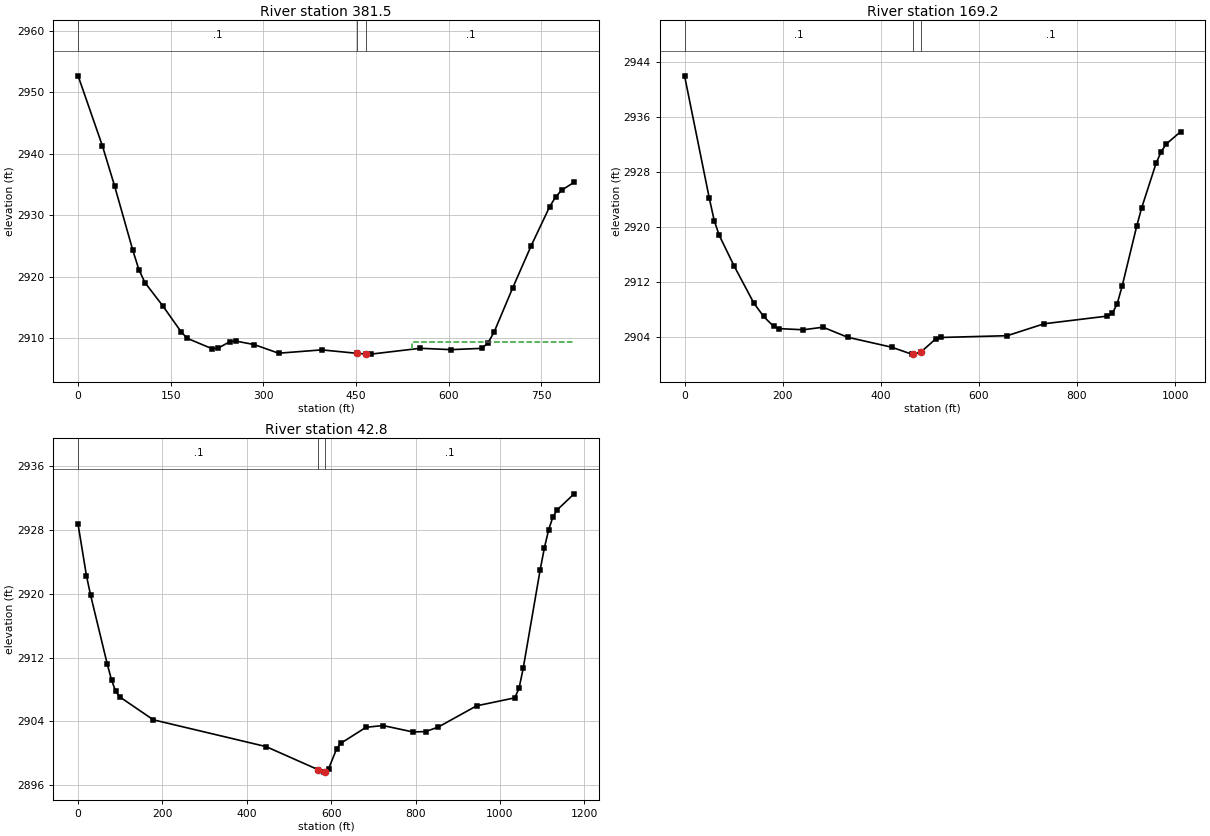
Type RM Length L Ch R = 1 ,381.5   ,191.9,212.3,232.7
XS GIS Cut Line= 3
     2087766.503      379638.557     2087478.169      379489.261
     2087115.625      379801.938
#Sta/Elev= 30
       0 2952.69    39.4 2941.28      59  2934.8    88.6  2924.3    98.4 2921.16
   108.2 2919.04   137.8 2915.16   167.3 2910.96   177.1 2909.95   216.5 2908.29
   226.3 2908.34     246 2909.42   255.8 2909.51   285.3 2908.94   324.7 2907.54
   394.5 2908.08   451.9 2907.52   466.9 2907.41   474.3 2907.39   554.1 2908.34
     604 2908.12   653.8 2908.33   663.8  2909.2   673.8 2910.99   703.7 2918.13
   733.6 2924.99   763.6 2931.36   773.5 2932.99   783.5  2934.1   803.4 2935.36
#Mann= 3 , 0 , 0
       0      .1       0   451.9    .045       0   466.9      .1       0
#XS Ineff= 2 , 0
       0  256.86 2909.32     541       0 2909.32
Permanent Ineff=
       F       F
Bank Sta=451.9,466.9
XS Rating Curve= 0 ,0
Exp/Cntr=0.3,0.1

Type RM Length L Ch R = 1 ,169.2   ,138.2,126.4,101.5
XS GIS Cut Line= 6
     2087767.925      379607.912     2087506.895      379401.835
     2087319.553      379369.362     2087315.806      379485.515
     2087293.325      379576.688     2087102.236      379779.017
#Sta/Elev= 30
       0 2942.02    50.4 2924.24    60.5 2920.98    70.6 2918.85   100.8 2914.42
   141.1 2909.01   161.2 2907.05   181.4 2905.62   191.5 2905.29   241.9 2905.12
   282.2 2905.49   332.6 2904.03   422.6 2902.58   462.7 2901.58     466 2901.58
     481 2901.84   512.7 2903.84   522.7    2904   657.7 2904.26   732.8 2905.99
     862 2907.11     872  2907.5   881.9 2908.93   891.8 2911.42   921.7  2920.2
   931.6 2922.81   961.4 2929.38   971.4 2930.96   981.3 2932.08  1011.1  2933.9
#Mann= 3 , 0 , 0
       0      .1       0     466    .045       0     481      .1       0
Bank Sta=466,481
XS Rating Curve= 0 ,0
Exp/Cntr=0.3,0.1

Type RM Length L Ch R = 1 ,42.8    ,39.8,42.8,58.9
XS GIS Cut Line= 6
     2087787.909      379562.949      2087596.82      379285.683
     2087372.009      379249.463     2087318.304      379305.666
     2087250.861      379600.418     2087087.249       379764.03
#Sta/Elev= 30
       0  2928.7    19.8 2922.27    29.7 2919.82    69.3 2911.16    79.2 2909.22
    89.1 2907.77      99 2907.07   178.3 2904.21   445.6 2900.85   569.7 2897.94
   583.9 2897.65   584.7 2897.68   593.6 2898.04     613 2900.59   622.8 2901.27
   682.5 2903.27   722.8 2903.49   793.4 2902.69   823.6 2902.73   853.8  2903.3
   944.6 2905.96  1035.1 2906.96  1045.2 2908.14  1055.2 2910.69  1095.4 2923.03
  1105.5  2925.8  1115.6 2928.06  1125.6 2929.65  1135.7 2930.53  1175.9 2932.54
#Mann= 3 , 0 , 0
       0      .1       0   569.7    .045       0   584.7      .1       0
Bank Sta=569.7,584.7
XS Rating Curve= 0 ,0
Exp/Cntr=0.3,0.1

Chan Stop Cuts=-1
Use User Specified Reach Order=0